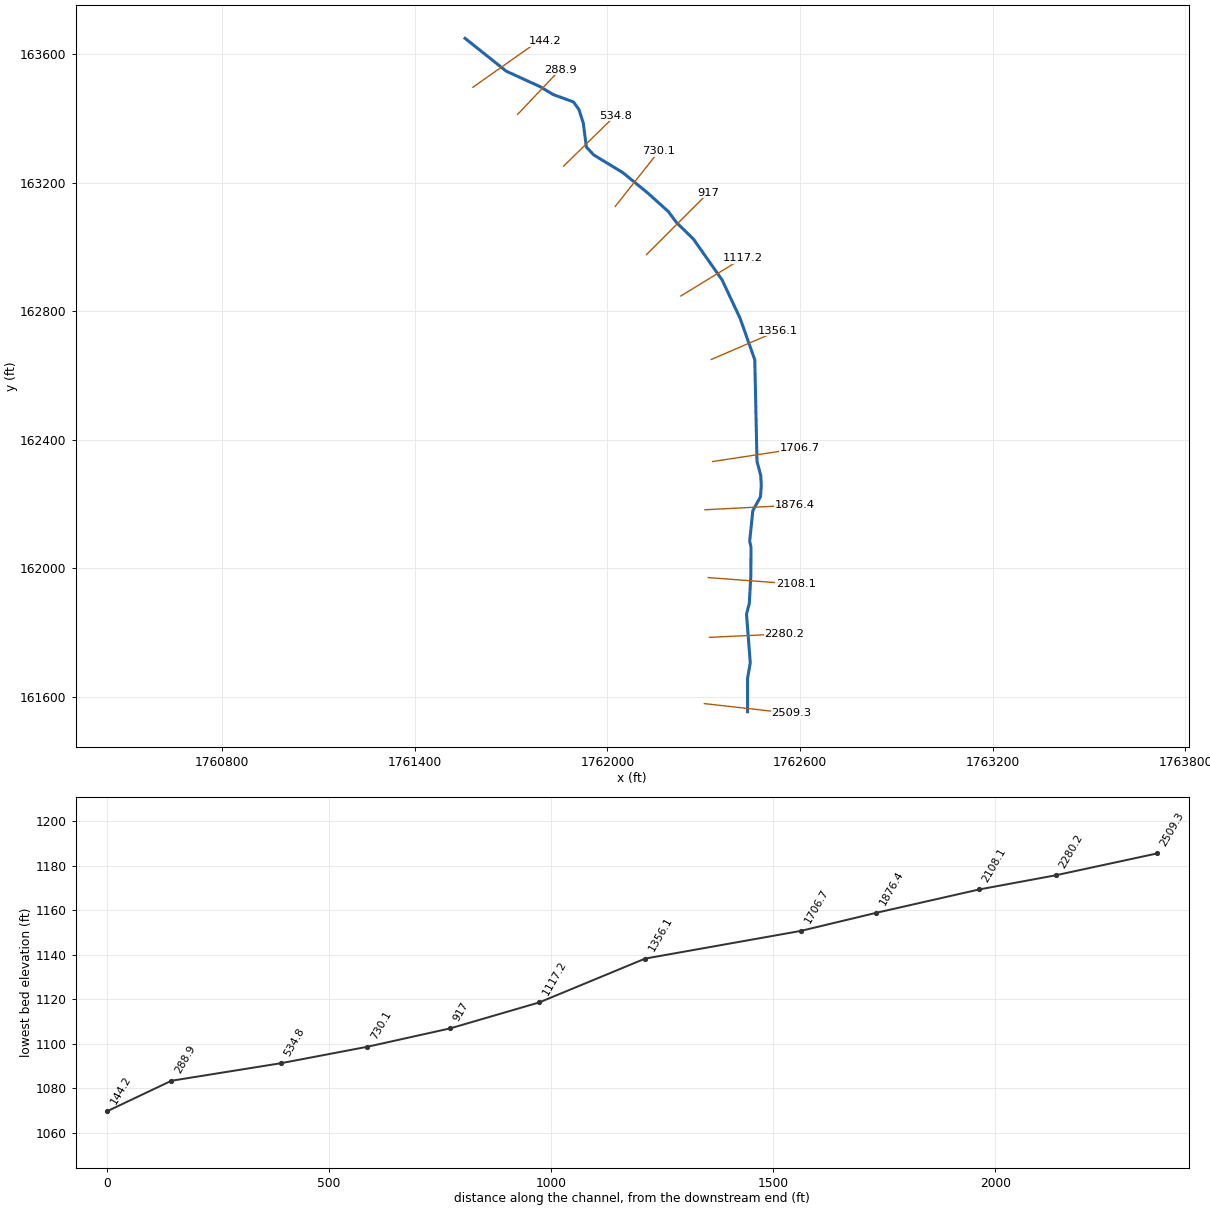
--- River Laurel Branch.prj (project) ---

Proj Title=River Laurel Branch
Current Plan=p01
Default Exp/Contr=0,0
English Units
Geom File=g01
Flow File=f01
Plan File=p01
BEGIN DESCRIPTION:
END DESCRIPTION:
DSS Export Rating Curves= 0
DSS Export Rating Curve Sorted= 0
DSS Export Volume Flow Curves= 0
DXF OffsetX= 0
DXF OffsetY= 0
DXF ScaleX= 0
DXF ScaleY= 0

--- River Laurel Branch.p01 (plan) ---

Plan Title=Floodplain
Program Version=4.00
Geom File=g01
Flow File=f01
K Sum by GR=0
Std Step Tol=0.01
Critical Tol=0.01
Num of Std Step Trials=20
Max Error Tol=0.3
Flow Tol Ratio=0.001
Split Flow NTrial=30
Split Flow Tol=0.02
Split Flow Ratio=0.02
Log Output Level=0
Friction Slope Method=1
Unsteady Friction Slope Method=2
Unsteady Bridges Friction Slope Method=1
Global Log Level=0
CheckData=False
Run HTab=0
Run UNet=0
Run PostProcess=0
UNET Theta=0
UNET Theta Warmup=0
UNET ZTol=0
UNET ZSATol=0
UNET MxIter=0
UNET MaxInSteps=0
UNET DtIC=0
UNET DtMin=0
UNET MaxCRTS=0
UNET WFStab=0
UNET SFStab=0
UNET WFX=0
UNET SFX=0
UNET DSS MLevel=0
UNET DZMax Abort=0
UNET Convert EG Bridges=0
UNET Use Existing IB Tables=0
UNET Froude Limit=0
UNET Froude Power=0
Write IC File=0
Echo Input=False
Echo Output=False
Write Detailed=0

--- River Laurel Branch.f01 (steady flow) ---

Flow Title=NFF Regression Equation
Program Version=4.00
Number of Profiles=1
Profile Names=P100yr
River Rch & RM=River Laurel ...,Main      ,2509.3
611.5894
River Rch & RM=River Laurel ...,Main      ,288.9
641.3821
Boundary for River Rch & Prof#=River Laurel ...,Main      ,1
Up Type=0
Dn Type=3
Dn Slope=0.054848

--- River Laurel Branch.g01 (geometry) ---

Geom Title=Geometry
Program Version=4.00

River Reach=River Laurel ...,Main
Reach XY= 30
     1762436.556      161553.318     1762436.584      161657.035
     1762445.044      161705.917     1762433.306      161856.954
     1762442.005      161890.505     1762446.649      161975.024
     1762447.446       162065.11     1762443.138      162084.185
     1762452.971      162179.229     1762476.839      162222.815
     1762479.325      162257.303     1762477.541      162289.406
     1762465.984      162332.316     1762459.026      162649.267
     1762413.412      162778.246     1762357.449      162897.597
     1762268.271      163024.824     1762215.513      163076.394
     1762189.688      163111.095     1762125.234      163168.995
     1762047.669      163232.358     1761957.378       163287.24
     1761934.595      163311.776     1761925.013      163385.827
     1761911.561      163428.501      1761894.32      163452.281
     1761831.078      163475.262      1761790.28      163499.843
      1761685.05      163547.998     1761556.843      163650.236

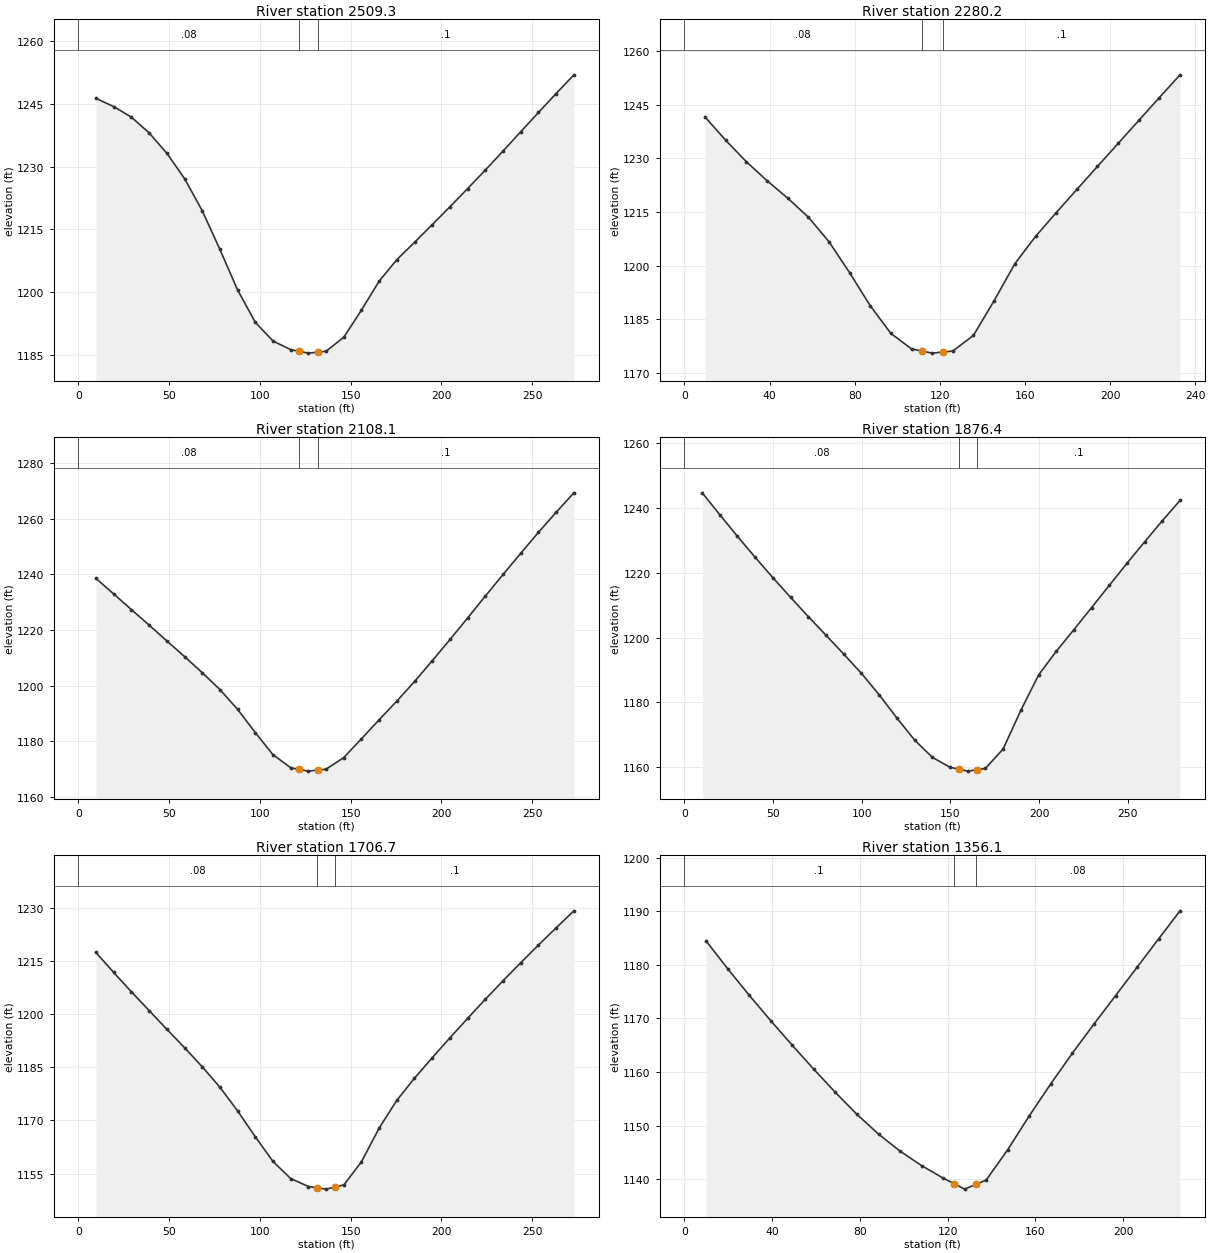
Type RM Length L Ch R = 1 ,2509.3  ,225.9,229.1,232.2
XS GIS Cut Line= 3
     1762302.015      161578.438     1762437.668      161563.256
     1762573.321      161548.074
#Sta/Elev= 30
     9.8 1246.32    19.5 1244.35    29.2 1241.85      39 1238.08    48.8 1233.19
    58.5 1227.17    68.2 1219.52      78 1210.23    87.7 1200.57    97.5  1192.8
   107.3 1188.32     117 1186.28   121.8 1185.86   126.7 1185.44   131.8 1185.67
   136.5 1185.89   146.3 1189.26     156 1195.74   165.7 1202.63   175.5  1207.8
   185.3 1211.95     195 1216.16   204.8 1220.45   214.5 1224.78   224.2 1229.18
     234 1233.74   243.8 1238.38   253.5 1242.96   263.2 1247.47     273 1251.95
#Mann= 3 , 0 , 0
       0     .08       0   121.8    .045       0   131.8      .1       0
Bank Sta=121.8,131.8
XS Rating Curve= 0 ,0
Exp/Cntr=0.3,0.1

Type RM Length L Ch R = 1 ,2280.2  ,174.6,172.2,169.7
XS GIS Cut Line= 2
     1762318.101      161784.892     1762550.731      161795.629
#Sta/Elev= 26
     9.7 1241.52    19.4 1235.05    29.1 1229.05    38.8 1223.76    48.5  1218.9
    58.2 1213.59    67.9 1206.73    77.6 1198.07    87.3 1188.82      97  1181.1
   106.7 1176.77   111.4  1176.2   116.4 1175.59   121.4 1175.89   126.1 1176.18
   135.8 1180.53   145.5 1190.22   155.3 1200.61     165  1208.2   174.7 1214.83
   184.4 1221.32   194.1 1227.75   203.8 1234.17   213.5 1240.59   223.2    1247
   232.9 1253.34
#Mann= 3 , 0 , 0
       0     .08       0   111.4    .045       0   121.4      .1       0
Bank Sta=111.4,121.4
XS Rating Curve= 0 ,0
Exp/Cntr=0.3,0.1

Type RM Length L Ch R = 1 ,2108.1  ,227.9,231.6,235.4
XS GIS Cut Line= 3
       1762314.3      161970.929      1762450.42      161960.743
     1762586.539      161950.557
#Sta/Elev= 30
     9.7 1238.54    19.5 1232.92    29.2 1227.33      39 1221.73    48.7 1216.09
    58.5 1210.43    68.2 1204.67      78 1198.56    87.8  1191.4    97.5 1183.09
   107.2 1175.16     117 1170.44   121.8 1169.84   126.7 1169.23   131.8  1169.6
   136.5 1169.93   146.2 1174.09     156 1180.86   165.7 1187.69   175.5 1194.42
   185.3  1201.5     195 1208.93   204.8 1216.57   214.5 1224.33   224.2 1232.14
     234 1239.93   243.8  1247.6   253.5 1255.09   263.3 1262.32     273 1269.28
#Mann= 3 , 0 , 0
       0     .08       0   121.8    .045       0   131.8      .1       0
Bank Sta=121.8,131.8
XS Rating Curve= 0 ,0
Exp/Cntr=0.3,0.1

Type RM Length L Ch R = 1 ,1876.4  ,168.8,169.7,170.6
XS GIS Cut Line= 2
     1762303.785      162182.154     1762582.942      162196.469
#Sta/Elev= 30
      10  1244.7      20 1237.89    29.9 1231.24    39.9 1224.76    49.9 1218.47
    59.9 1212.38    69.9 1206.44    79.9 1200.66    89.8 1194.91    99.8 1188.94
   109.8 1182.32   119.8 1175.15   129.8 1168.33   139.8 1163.01   149.7 1159.94
   154.7 1159.34   159.7 1158.74   164.7 1159.16   169.7 1159.57   179.7 1165.56
   189.7  1177.5   199.7 1188.42   209.6  1195.7   219.6 1202.41   229.6 1209.26
   239.6 1216.12   249.6 1222.94   259.6 1229.61   269.5 1236.07   279.5 1242.36
#Mann= 3 , 0 , 0
       0     .08       0   154.7    .045       0   164.7      .1       0
Bank Sta=154.7,164.7
XS Rating Curve= 0 ,0
Exp/Cntr=0.3,0.1

Type RM Length L Ch R = 1 ,1706.7  ,345.4,350.6,355.7
XS GIS Cut Line= 3
     1762327.902      162332.382     1762462.849      162352.918
     1762597.795      162373.454
#Sta/Elev= 30
     9.7 1217.44    19.5 1211.79    29.2 1206.35      39 1201.05    48.7  1195.8
    58.5 1190.57    68.2 1185.21      78  1179.4    87.7 1172.75    97.5  1165.4
   107.2 1158.46     117  1153.6   126.8 1151.36   131.5    1151   136.5 1150.62
   141.5 1151.23   146.3 1151.82     156 1158.37   165.8 1167.92   175.5 1175.72
   185.2 1181.95     195 1187.72   204.7 1193.33   214.5 1198.84   224.2 1204.21
     234 1209.47   243.8 1214.58   253.5 1219.56   263.3 1224.42     273  1229.2
#Mann= 3 , 0 , 0
       0     .08       0   131.5    .045       0   141.5      .1       0
Bank Sta=131.5,141.5
XS Rating Curve= 0 ,0
Exp/Cntr=0.3,0.1

Type RM Length L Ch R = 1 ,1356.1  ,236.1,238.9,241.8
XS GIS Cut Line= 2
     1762323.699      162650.192     1762531.277      162739.665
#Sta/Elev= 25
     9.8 1184.47    19.7 1179.27    29.5 1174.33    39.3  1169.6    49.1 1165.02
      59 1160.52    68.8 1156.22    78.6 1152.14    88.5 1148.43    98.3 1145.27
   108.1 1142.58   117.9 1140.25   122.8 1139.22   127.8 1138.18   132.8 1139.05
   137.6 1139.88   147.4 1145.52   157.2 1151.81   167.1 1157.84   176.9 1163.52
   186.7 1168.92   196.6 1174.25   206.4 1179.54   216.2 1184.82     226 1190.06
#Mann= 3 , 0 , 0
       0      .1       0   122.8    .045       0   132.8     .08       0
Bank Sta=122.8,132.8
XS Rating Curve= 0 ,0
Exp/Cntr=0.3,0.1

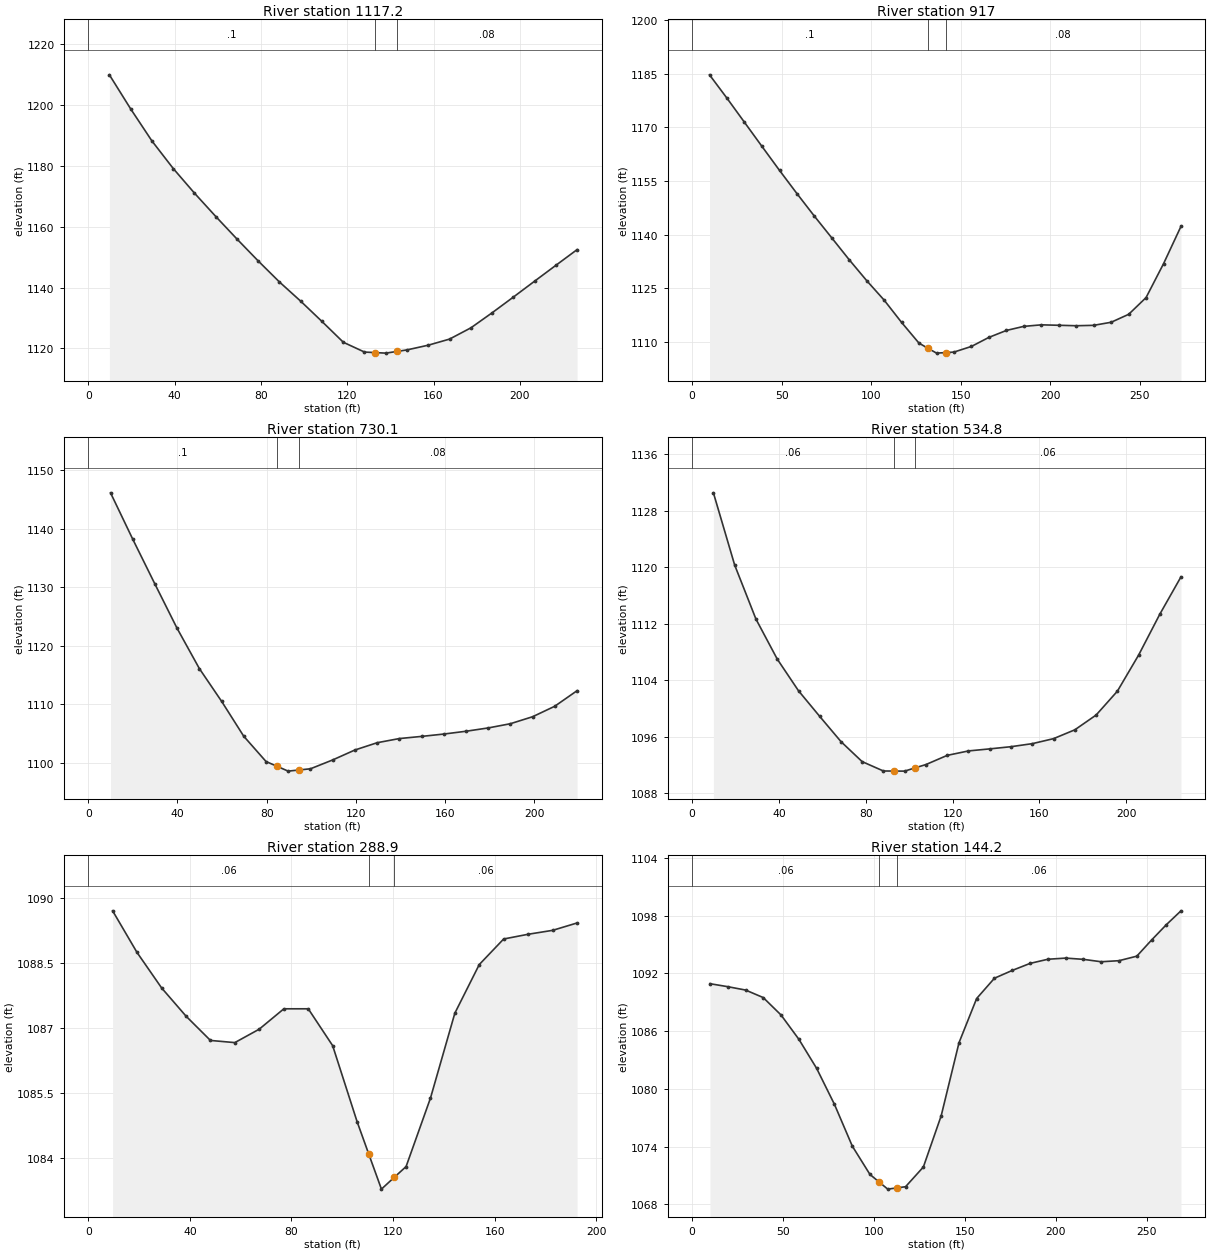
Type RM Length L Ch R = 1 ,1117.2  ,195.5,200.2,205
XS GIS Cut Line= 2
     1762228.627      162847.836      1762421.89       162965.94
#Sta/Elev= 25
     9.8 1209.94    19.7  1198.7    29.5 1188.22    39.4 1179.13    49.2 1171.07
    59.1 1163.37    68.9 1155.98    78.8 1148.73    88.6 1141.85    98.5  1135.5
   108.3 1128.87   118.2 1122.03     128 1118.81   132.9 1118.64   137.9 1118.46
   142.9    1119   147.7 1119.52   157.6 1121.08   167.4 1123.07   177.3 1126.77
   187.1  1131.7     197 1136.89   206.8  1142.1   216.6 1147.28   226.5 1152.48
#Mann= 3 , 0 , 0
       0      .1       0   132.9    .045       0   142.9     .08       0
Bank Sta=132.9,142.9
XS Rating Curve= 0 ,0
Exp/Cntr=0.3,0.1

Type RM Length L Ch R = 1 ,917     ,184.6,186.9,189.2
XS GIS Cut Line= 3
     1762121.963      162976.903     1762218.483      163073.424
     1762315.002      163169.944
#Sta/Elev= 30
     9.7 1184.74    19.5 1178.17    29.2 1171.47      39  1164.7    48.8 1157.98
    58.5 1151.51    68.2 1145.22      78 1139.08    87.7 1132.98    97.5 1127.11
   107.2 1121.68     117  1115.4   126.7 1109.61   131.5 1108.24   136.5 1106.82
   141.5 1106.97   146.2 1107.11     156  1108.7   165.7 1111.22   175.5 1113.17
   185.2 1114.31     195 1114.74   204.7 1114.62   214.5 1114.49   224.2  1114.6
     234 1115.46   243.8 1117.69   253.5 1122.37   263.3 1131.89     273 1142.31
#Mann= 3 , 0 , 0
       0      .1       0   131.5    .045       0   141.5     .08       0
Bank Sta=131.5,141.5
XS Rating Curve= 0 ,0
Exp/Cntr=0.3,0.1

Type RM Length L Ch R = 1 ,730.1   ,196.2,195.3,194.4
XS GIS Cut Line= 2
     1762024.628      163126.992     1762160.627      163298.781
#Sta/Elev= 24
      10 1146.15    19.9 1138.26    29.9 1130.54    39.8 1122.99    49.8 1116.09
    59.8 1110.47    69.7 1104.51    79.7 1100.18    84.6 1099.37    89.6 1098.54
    94.6 1098.74    99.6 1098.94   109.6 1100.46   119.5 1102.15   129.5  1103.4
   139.4 1104.11   149.4 1104.48   159.3 1104.88   169.3 1105.36   179.3 1105.93
   189.2 1106.65   199.2 1107.85   209.1 1109.64   219.1  1112.3
#Mann= 3 , 0 , 0
       0      .1       0    84.6    .045       0    94.6     .08       0
Bank Sta=84.6,94.6
XS Rating Curve= 0 ,0
Exp/Cntr=0.3,0.1

Type RM Length L Ch R = 1 ,534.8   ,246.8,245.8,244.9
XS GIS Cut Line= 2
     1761863.576      163252.255     1762024.628      163409.728
#Sta/Elev= 25
     9.8 1130.54    19.6 1120.31    29.4 1112.66    39.2    1107      49 1102.51
    58.8 1098.87    68.6  1095.3    78.3 1092.48    88.1 1091.15    92.9 1091.14
    97.9 1091.13   102.9 1091.61   107.7 1092.06   117.5 1093.36   127.3 1093.99
   137.1 1094.28   146.9 1094.59   156.7 1095.02   166.5 1095.73   176.3 1096.98
   186.1 1099.07   195.9 1102.45   205.7 1107.57   215.5 1113.38   225.2 1118.64
#Mann= 3 , 0 , 0
       0     .06       0    92.9    .045       0   102.9     .06       0
Bank Sta=92.9,102.9
XS Rating Curve= 0 ,0
Exp/Cntr=0.3,0.1

Type RM Length L Ch R = 1 ,288.9   ,148.8,144.7,140.6
XS GIS Cut Line= 2
     1761720.418      163413.307     1761852.839      163552.886
#Sta/Elev= 22
     9.6  1089.7    19.2 1088.74    28.9 1087.92    38.5 1087.27    48.1 1086.71
    57.7 1086.66    67.3 1086.97      77 1087.44    86.6 1087.44    96.2 1086.59
   105.8 1084.84   110.4 1084.09   115.4 1083.28   120.4 1083.55   125.1  1083.8
   134.7 1085.38   144.3 1087.34   153.9 1088.46   163.5 1089.05   173.2 1089.16
   182.8 1089.25   192.4 1089.42
#Mann= 3 , 0 , 0
       0     .06       0   110.4    .045       0   120.4     .06       0
Bank Sta=110.4,120.4
XS Rating Curve= 0 ,0
Exp/Cntr=0.3,0.1

Type RM Length L Ch R = 1 ,144.2   ,139,144.2,149.5
XS GIS Cut Line= 3
      1761581.19      163497.825      1761781.11      163638.752
     1761805.144      163642.029
#Sta/Elev= 30
     9.8 1090.92    19.6 1090.61    29.4 1090.26    39.1 1089.48    48.9 1087.67
    58.7 1085.15    68.5 1082.12    78.3 1078.38    88.1 1074.05    97.8 1071.11
   102.6 1070.36   107.6 1069.58   112.6 1069.71   117.4 1069.83   127.2 1071.88
     137  1077.2   146.8 1084.79   156.5 1089.38   166.3 1091.49   176.1  1092.3
   185.9 1093.03   195.7 1093.46   205.5 1093.58   215.2 1093.45     225  1093.2
   234.8 1093.31   244.6 1093.78   252.7 1095.45   260.8 1097.04   268.9 1098.49
#Mann= 3 , 0 , 0
       0     .06       0   102.6    .045       0   112.6     .06       0
Bank Sta=102.6,112.6
XS Rating Curve= 0 ,0
Exp/Cntr=0.3,0.1

Chan Stop Cuts=-1
Use User Specified Reach Order=0